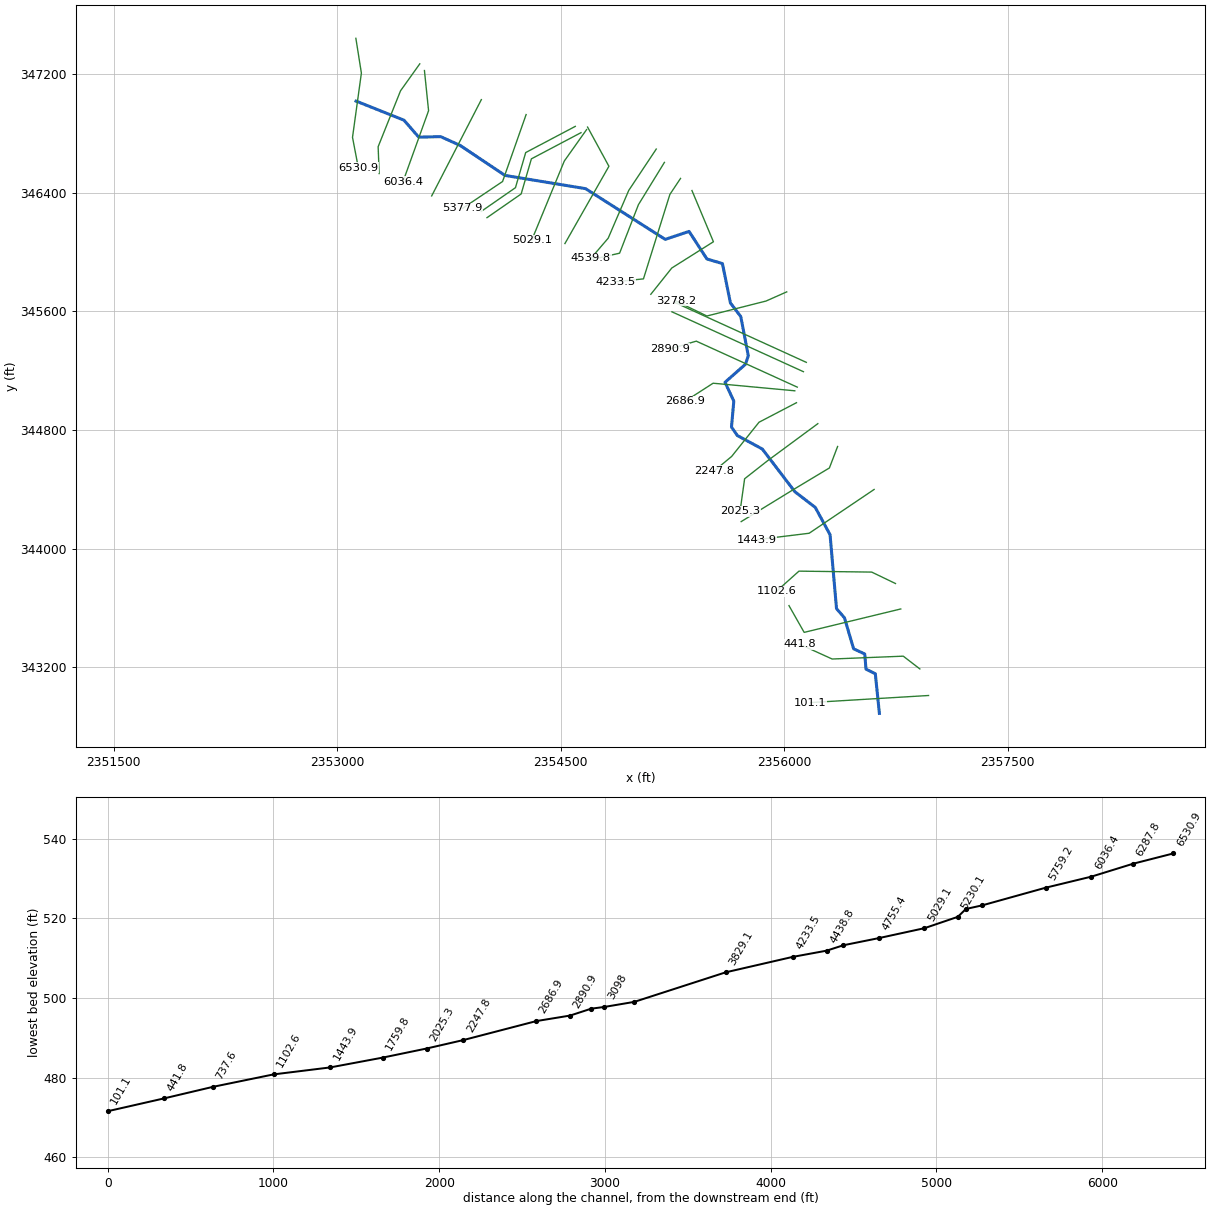
--- BACKTRIB3.prj (project) ---

Proj Title=BACKTRIB3
Current Plan=p01
Default Exp/Contr=0,0
English Units
Geom File=g01
Flow File=f01
Plan File=p01
BEGIN DESCRIPTION:
END DESCRIPTION:
DSS Export Rating Curves= 0
DSS Export Rating Curve Sorted= 0
DSS Export Volume Flow Curves= 0
DXF OffsetX= 0
DXF OffsetY= 0
DXF ScaleX= 0
DXF ScaleY= 0

--- BACKTRIB3.p01 (plan) ---

Plan Title=Floodplain
Program Version=4.00
Geom File=g01
Flow File=f01
K Sum by GR=0
Std Step Tol=0.01
Critical Tol=0.01
Num of Std Step Trials=20
Max Error Tol=0.3
Flow Tol Ratio=0.001
Split Flow NTrial=30
Split Flow Tol=0.02
Split Flow Ratio=0.02
Log Output Level=0
Friction Slope Method=1
Unsteady Friction Slope Method=2
Unsteady Bridges Friction Slope Method=1
Global Log Level=0
CheckData=False
Run HTab=0
Run UNet=0
Run PostProcess=0
UNET Theta=0
UNET Theta Warmup=0
UNET ZTol=0
UNET ZSATol=0
UNET MxIter=0
UNET MaxInSteps=0
UNET DtIC=0
UNET DtMin=0
UNET MaxCRTS=0
UNET WFStab=0
UNET SFStab=0
UNET WFX=0
UNET SFX=0
UNET DSS MLevel=0
UNET DZMax Abort=0
UNET Convert EG Bridges=0
UNET Use Existing IB Tables=0
UNET Froude Limit=0
UNET Froude Power=0
Write IC File=0
Echo Input=False
Echo Output=False
Write Detailed=0

--- BACKTRIB3.f01 (steady flow) ---

Flow Title=NFF Regression Equation
Program Version=4.00
Number of Profiles=1
Profile Names=P100yr
River Rch & RM=BACKTRIB3,Main      ,6530.9
831.4343
River Rch & RM=BACKTRIB3,Main      ,441.8
907.4338
River Rch & RM=BACKTRIB3,Main      ,101.1
909.9403
Boundary for River Rch & Prof#=BACKTRIB3,Main      ,1
Up Type=0
Dn Type=3
Dn Slope=0.009278

--- BACKTRIB3.g01 (geometry) ---

Geom Title=USGS 10m DEM
Program Version=4.10

River Reach=BACKTRIB3       ,Main
Reach XY= 30
     2353127.245      347018.395     2353448.425      346889.923
     2353547.717      346775.388     2353694.953      346778.812
     2353825.161      346719.784     2354126.536      346517.402
     2354667.175      346428.117     2355201.897      346086.103
      2355361.62      346139.923     2355481.411      345954.159
     2355585.578      345922.909     2355639.398      345657.284
     2355708.842       345565.27     2355759.189      345301.381
     2355740.092       345244.09     2355602.939      345122.562
     2355661.967      344995.826     2355646.342      344820.479
     2355686.272      344763.187     2355852.939      344672.909
     2356071.589      344384.871     2356208.842      344278.812
       2356307.8      344094.784     2356351.203       343596.52
     2356404.488      343534.611     2356465.786      343325.687
     2356540.439      343290.965      2356549.12      343188.534
      2356611.62      343157.284     2356638.791      342890.413

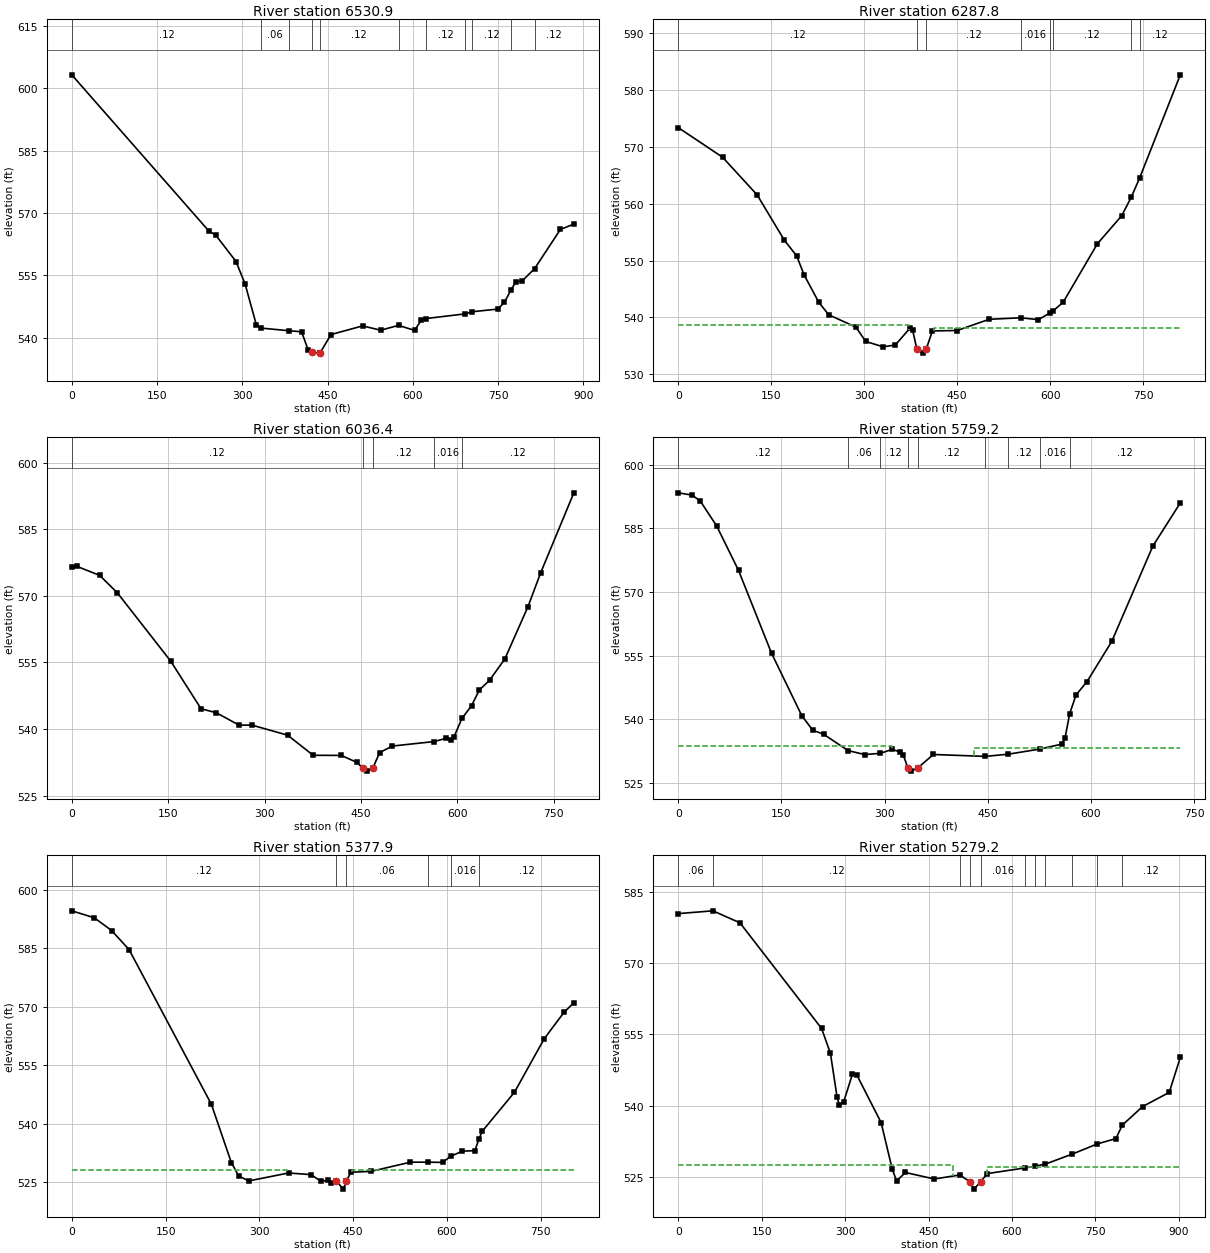
Type RM Length L Ch R = 1 ,6530.9  ,248.6,243.1,237.6
XS GIS Cut Line= 4
     2353125.897      347441.599     2353162.864      347207.273
     2353103.328      346774.064      2353142.39      346569.203
#Sta/Elev= 30
       0  603.25   241.2  565.68   253.1  564.73   288.9  558.36   304.8  552.98
   324.7  543.11  333.24542.3464  382.38541.7136   404.2  541.46   416.1  536.99
   421.7   536.6     436  536.33   436.7  536.38   455.9  540.79   511.5  542.88
   543.3  541.84  574.71 543.003     603   541.8   614.9  544.31  622.43544.6371
   692.4 545.776  703.79546.2753   749.3  546.92   761.1  548.55  772.44551.5009
   780.8  553.41   792.6  553.76  813.93556.6195   859.4  566.06   883.1  567.36
#Mann= 11 ,-1 , 0
       0     .12       0  333.24     .06       0  382.38     .12       0
   421.7    .045       0   436.7     .12       0  574.71    .016       0
  622.43     .12       0   692.4     .06       0  703.79     .12       0
  772.44     .06       0  813.93     .12       0
Bank Sta=421.7,436.7
XS Rating Curve= 0 ,0
Exp/Cntr=0.3,0.1

Type RM Length L Ch R = 1 ,6287.8  ,250.6,251.4,251.8
XS GIS Cut Line= 4
     2353554.716      347269.724     2353425.661      347088.016
       2353275.3      346711.009     2353282.147      346530.141
#Sta/Elev= 30
       0  573.35    71.6  568.14   127.4  561.51   171.1  553.58     191  550.82
     203  547.49   226.8  542.64   242.8  540.47   286.5  538.31   302.5  535.79
   330.3  534.85   350.2  535.17   374.1  538.17   378.1  537.74  384.98   534.4
     394  533.74  399.95  534.43   409.9  537.64   449.7  537.71   501.4  539.68
   552.2 539.945     581  539.62  599.22 540.787  603.79541.0812   620.8  542.66
     676  552.94   715.3  557.88  730.54561.0902  744.43564.5694   809.8  582.62
#Mann= 8 ,-1 , 0
       0     .12       0  384.98    .045       0  399.95     .12       0
   552.2    .016       0  599.22     .06       0  603.79     .12       0
  730.54     .06       0  744.43     .12       0
#XS Ineff= 2 , 0
          371.52  538.72   412.8          538.11
Permanent Ineff=
       F       F
Bank Sta=384.98,399.95
XS Rating Curve= 0 ,0
Exp/Cntr=0.3,0.1

Type RM Length L Ch R = 1 ,6036.4  ,280.3,277.3,274.2
XS GIS Cut Line= 3
     2353585.966      347224.585     2353613.744      346953.752
     2353441.869      346474.585
#Sta/Elev= 30
       0   576.4     7.9  576.65    43.4  574.62      71  570.67   153.9   555.3
   201.2  544.55   224.9  543.66   260.4  540.86   280.2  540.88   335.9   538.6
   375.7  534.07   419.4  534.04   443.3  532.49  452.96  531.18   459.2   530.5
  468.49  531.18   479.1  534.68   498.9  536.15   563.9 537.165   582.5   537.9
   590.4  537.49   594.4  538.08  607.13 542.376   622.2  545.27   634.2  548.78
   650.1  550.97   673.9  555.78   709.7  567.49   729.6  575.17   781.3  593.22
#Mann= 5 ,-1 , 0
       0     .12       0  452.96    .045       0  468.49     .12       0
   563.9    .016       0  607.13     .12       0
Bank Sta=452.96,468.49
XS Rating Curve= 0 ,0
Exp/Cntr=0.3,0.1

Type RM Length L Ch R = 1 ,5759.2  ,378.4,381.3,384.2
XS GIS Cut Line= 2
     2353967.911      347028.404     2353634.578      346379.099
#Sta/Elev= 30
       0  593.42    19.9  592.89    31.9  591.51    55.8  585.62    87.7  575.08
   135.6  555.56   179.5  540.83   195.4  537.38   211.4   536.4  246.92532.5428
   271.2  531.61  293.65531.9025   311.1  532.83   323.1  532.19     327   531.6
   333.9  528.43     339   527.7   348.9  528.55   370.9  531.63   446.6531.1795
  479.98531.7048  525.81532.9141   558.4  534.11   562.4  535.64  569.17541.3083
   578.3  545.68   594.3  548.85   630.2  558.32     690  580.85   729.9  591.04
#Mann= 9 ,-1 , 0
       0     .12       0  246.92     .06       0  293.65     .12       0
   333.9    .045       0   348.9     .12       0   446.6     .06       0
  479.98     .12       0  525.81    .016       0  569.17     .12       0
#XS Ineff= 2 , 0
          311.25  533.65  430.13          533.11
Permanent Ineff=
       F       F
Bank Sta=333.9,348.9
XS Rating Curve= 0 ,0
Exp/Cntr=0.3,0.1

Type RM Length L Ch R = 1 ,5377.9  ,97.5,98.7,99.8
XS GIS Cut Line= 3
     2354268.258       346927.71     2354110.272      346476.321
     2353841.175      346294.898
#Sta/Elev= 30
       0  594.59    35.9  592.82    63.8  589.53    91.7  584.63   223.2  545.03
   255.1   530.1     267  526.64     283  525.38   346.7  527.42   382.6  526.99
   398.5  525.28   410.5  525.55   414.5  524.78   422.4  525.44   434.4  523.28
  439.25  525.45   446.4  527.61   478.2  527.82   541.6  530.19  569.29  530.18
     593  530.14  606.16531.7283   624.7  533.01   644.5  533.13  651.19536.1764
   656.3   538.1   707.8  548.09   755.3  561.78     787  568.57   802.8  571.04
#Mann= 6 ,-1 , 0
       0     .12       0   422.4    .045       0  439.25     .06       0
  569.29     .12       0  606.16    .016       0  651.19     .12       0
#XS Ineff= 2 , 0
          344.69  528.24  447.88          528.24
Permanent Ineff=
       F       F
Bank Sta=422.4,439.25
XS Rating Curve= 0 ,0
Exp/Cntr=0.3,0.1

Type RM Length L Ch R = 1 ,5279.2  ,48.8,49.1,48.8
XS GIS Cut Line= 4
     2354598.206      346847.936      2354265.48       346671.46
      2354196.73      346434.654     2353967.564      346274.932
#Sta/Elev= 30
       0  580.47   62.39581.0563     111  578.52   257.7  556.25   273.6  551.01
   285.4  541.89   289.4  540.15   297.3  540.74   313.2  546.63   321.1  546.43
   364.7  536.41   384.6  526.64   392.5  524.08   408.4  525.88   460.2  524.51
  506.66525.3572   525.2  523.83   531.7  522.37   543.7  523.93   555.6  525.65
  623.73526.8427  641.64527.2215  660.13527.6509  708.68529.7736   753.4531.9063
   786.8  533.03  798.26535.8583   834.7  539.77   882.6  542.76   902.6  550.14
#Mann= 11 ,-1 , 0
       0     .06       0   62.39     .12       0  506.66    .016       0
   525.2    .045       0   543.7    .016       0  623.73     .06       0
  641.64    .016       0  660.13     .12       0  708.68     .06       0
   753.4    .016       0  798.26     .12       0
#XS Ineff= 2 , 0
          494.32  527.45  554.18          526.98
Permanent Ineff=
       F       F
Bank Sta=525.2,543.7
XS Rating Curve= 0 ,0
Exp/Cntr=0.3,0.1

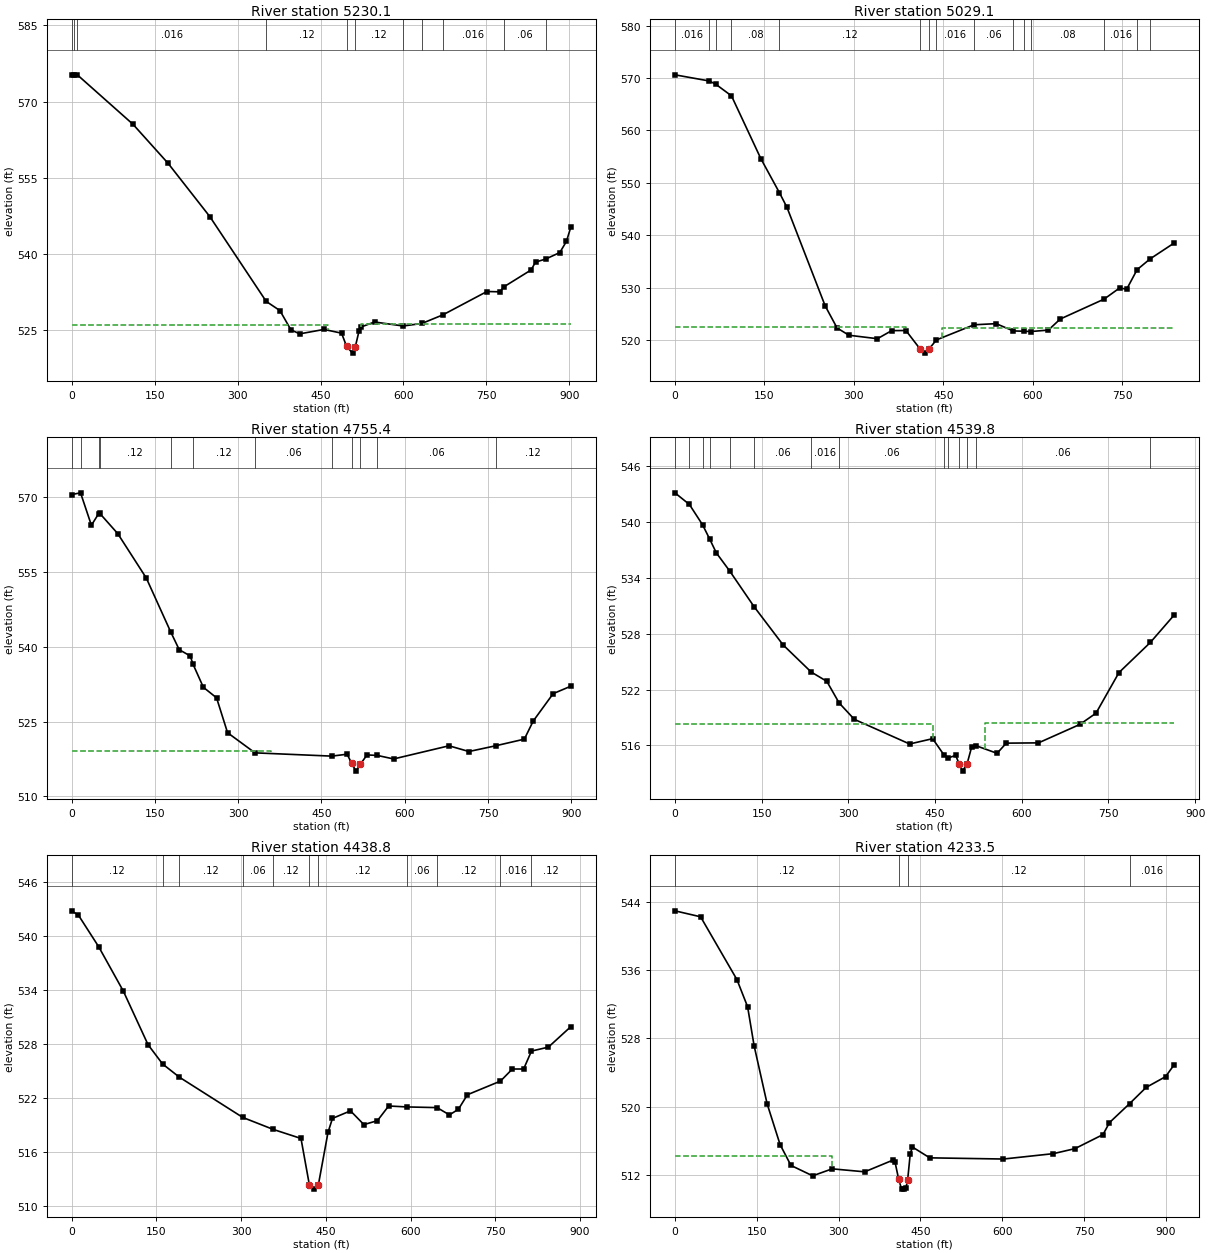
Type RM Length L Ch R = 1 ,5230.1  ,203.3,201.1,198.6
XS GIS Cut Line= 4
       2354636.4      346805.575     2354303.675      346629.099
     2354234.925      346392.293     2354005.758      346232.571
#Sta/Elev= 30
       0  575.27    4.42575.2665   10.32575.2656     111  565.51   174.4  557.82
   249.8  547.32  351.83530.5866   376.6  528.78   396.5  524.98   412.4  524.19
   456.2  525.06     488  524.33   497.2  521.71   507.9  520.39  512.96  521.67
   519.8  524.83   523.8  525.56   547.6  526.53  599.48525.7412  633.03526.2332
  671.14527.9307   750.9  532.54   774.8  532.48  780.91533.4218   830.7  536.79
   838.7  538.34  856.94538.9368   882.6  540.22   894.6  542.42   902.6  545.26
#Mann= 11 ,-1 , 0
       0    .016       0    4.42     .08       0   10.32    .016       0
  351.83     .12       0   497.2    .045       0  512.96     .12       0
  599.48     .06       0  633.03     .12       0  671.14    .016       0
  780.91     .06       0  856.94     .12       0
#XS Ineff= 2 , 0
          463.36  525.98  523.22          526.18
Permanent Ineff=
       F       F
Bank Sta=497.2,512.96
XS Rating Curve= 0 ,0
Exp/Cntr=0.3,0.1

Type RM Length L Ch R = 1 ,5029.1  ,276.5,273.6,270.8
XS GIS Cut Line= 3
     2354674.161      346826.408     2354524.421      346614.168
     2354305.671      346080.314
#Sta/Elev= 30
       0  570.61   57.02569.4472   68.01568.8514   94.72566.6025   143.9  554.64
  175.14548.1237   187.8  545.32   251.8  526.54   271.7  522.34   291.6  520.95
   339.3  520.29   363.2  521.83   387.1  521.85   410.5  518.38   418.9  517.54
   425.5  518.29  438.22520.0574  501.31522.9454   538.3  523.16  567.12521.7724
  585.45521.7142  596.59521.6635   625.8  521.93   645.7  524.04  719.19527.8365
   745.2  529.96   757.1  529.74  774.56533.4535  796.33535.5088   836.7  538.54
#Mann= 15 ,-1 , 0
       0    .016       0   57.02     .08       0   68.01     .06       0
   94.72     .08       0  175.14     .12       0   410.5    .045       0
   425.5     .12       0  438.22    .016       0  501.31     .06       0
  567.12     .08       0  585.45     .06       0  596.59     .08       0
  719.19    .016       0  774.56     .12       0  796.33     .06       0
#XS Ineff= 2 , 0
             387  522.53  447.88           522.3
Permanent Ineff=
       F       F
Bank Sta=410.5,425.5
XS Rating Curve= 0 ,0
Exp/Cntr=0.3,0.1

Type RM Length L Ch R = 1 ,4755.4  ,213.1,215.6,218.1
XS GIS Cut Line= 3
     2354680.671      346843.335       2354823.9      346579.012
     2354528.784      346058.124
#Sta/Elev= 30
       0   570.5   16.06570.8511    35.6  564.35    48.6 566.659    50.3 566.781
    83.1  562.67   134.5  553.77  178.27543.0179   193.8  539.41   213.6  538.15
   218.6536.5187   237.3  531.87   261.1  529.75   280.9  522.76  330.31518.7245
  468.66518.0672   496.2  518.45   504.2   516.7   512.2  515.06   520.2  516.45
   532.1  518.31  550.89 518.204     580   517.5   679.8  520.14   715.7  518.99
  763.81520.1411   815.5  521.47   831.5   525.1   867.4  530.59   899.3  532.09
#Mann= 12 ,-1 , 0
       0    .016       0   16.06     .08       0    48.6    .016       0
    50.3     .12       0  178.27    .016       0   218.6     .12       0
  330.31     .06       0  468.66     .12       0   504.2    .045       0
   520.2     .12       0  550.89     .06       0  763.81     .12       0
#XS Ineff= 2 , 0
          359.13   519.1
Permanent Ineff=
       F       F
Bank Sta=504.2,520.2
XS Rating Curve= 0 ,0
Exp/Cntr=0.3,0.1

Type RM Length L Ch R = 1 ,4539.8  ,100.2,101,101.8
XS GIS Cut Line= 4
     2355141.472       346694.95     2354956.902      346416.219
     2354818.986      346094.125     2354702.807      345957.918
#Sta/Elev= 30
       0  543.09      25541.8395   47.81539.6588   60.03538.1387    71.6  536.65
   95.05534.6783  136.81530.8894     187  526.79  235.68523.8756   262.7  522.88
  283.99 520.563   310.4   518.8     406  516.16   445.8  516.73  465.73514.9594
  472.86514.6646   485.6  514.94  491.88  514.01   497.6  513.25   505.5  514.06
   513.5  515.88  521.01515.9719   557.3  515.16   573.2  516.25   628.9  516.28
   700.6  518.26   728.4  519.46   768.2  523.82  822.43527.0452   863.7  529.99
#Mann= 14 ,-1 , 0
       0     .06       0      25     .08       0   47.81     .06       0
   60.03     .08       0   95.05    .016       0  136.81     .06       0
  235.68    .016       0  283.99     .06       0  465.73    .016       0
  472.86     .12       0  491.88    .045       0   505.5     .12       0
  521.01     .06       0  822.43     .12       0
#XS Ineff= 2 , 0
          445.82  518.34  536.64          518.45
Permanent Ineff=
       F       F
Bank Sta=491.88,505.5
XS Rating Curve= 0 ,0
Exp/Cntr=0.3,0.1

Type RM Length L Ch R = 1 ,4438.8  ,203.8,205.3,206.5
XS GIS Cut Line= 4
     2355196.296      346605.054     2355021.817      346319.898
     2354895.515      345993.075     2354701.505      345948.804
#Sta/Elev= 30
       0  542.82    11.9  542.35    47.8  538.84    91.5   533.9   135.3  527.94
  161.05525.7959  190.69 524.334  302.96 519.857  356.91518.5264     406  517.52
  420.87  512.35   429.9  511.89   436.7  512.34   453.8  518.19   461.7  519.75
   493.6  520.59   517.4  519.06   541.3   519.5   561.2  521.13  593.49521.0251
  646.92520.9496   668.8  520.14   684.7  520.77   700.6  522.38   759.1 523.896
   780.2  525.24   800.1  525.24  813.98527.2332   843.9  527.67   883.7  529.95
#Mann= 11 ,-1 , 0
       0     .12       0  161.05    .016       0  190.69     .12       0
  302.96     .06       0  356.91     .12       0  420.87    .045       0
   436.7     .12       0  593.49     .06       0  646.92     .12       0
   759.1    .016       0  813.98     .12       0
Bank Sta=420.87,436.7
XS Rating Curve= 0 ,0
Exp/Cntr=0.3,0.1

Type RM Length L Ch R = 1 ,4233.5  ,421.2,404.3,387.5
XS GIS Cut Line= 4
     2355304.369      346496.981      2355232.99       346389.24
     2355055.671      345819.898     2354866.869      345800.366
#Sta/Elev= 30
       0  542.96      47  542.26   113.6   534.9   133.2  531.71   145.1  527.15
     169  520.33   192.8  515.54   212.7   513.1   252.5  511.88   288.3   512.7
   347.9  512.35   399.6  513.72   403.6  513.47   410.2  511.48   415.5  510.33
   419.4  510.32   423.4  510.43  426.75  511.44   431.4  514.45   435.4  515.26
   467.2  513.99   602.3  513.85   693.8  514.48   733.5  515.07   784.9  516.72
   796.7  518.12  833.62520.3462     864  522.25   899.6  523.51   915.4  524.91
#Mann= 4 ,-1 , 0
       0     .12       0   410.2    .045       0  426.75     .12       0
  833.62    .016       0
#XS Ineff= 2 , 0
          287.93   514.2
Permanent Ineff=
       F       F
Bank Sta=410.2,426.75
XS Rating Curve= 0 ,0
Exp/Cntr=0.3,0.1

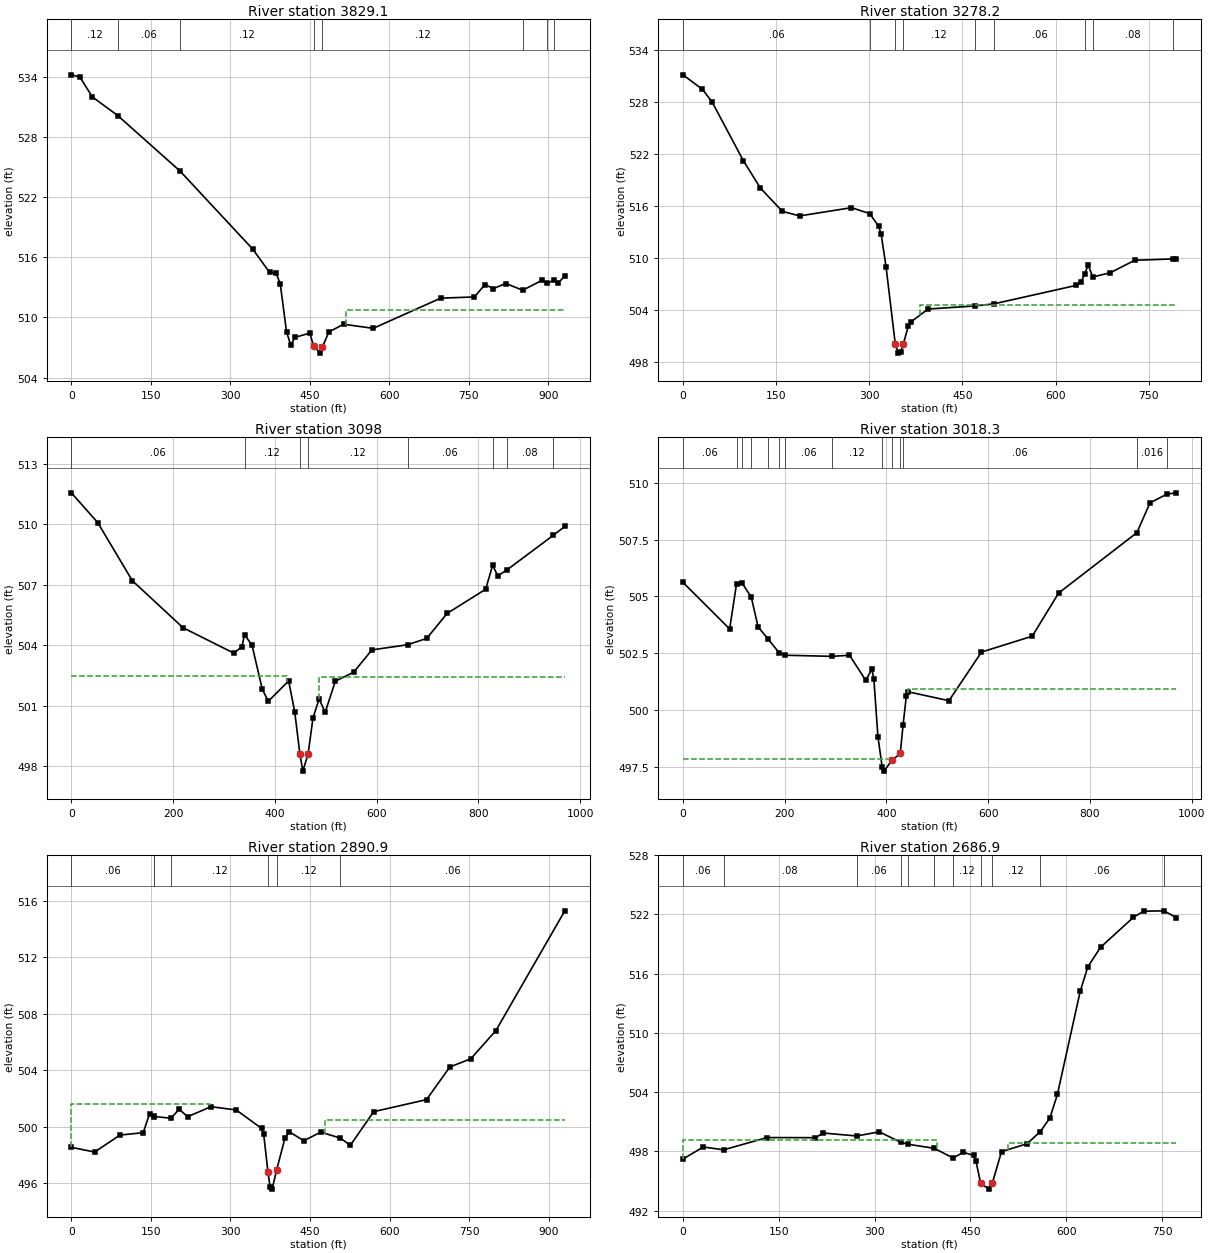
Type RM Length L Ch R = 1 ,3829.1  ,546,550.9,544.5
XS GIS Cut Line= 4
     2355381.105      346415.557     2355525.203      346070.071
     2355245.689      345892.988     2355105.064      345715.904
#Sta/Elev= 30
       0  534.18    15.9  533.97    39.8  531.97   87.48530.1257  205.14524.5882
   342.5   516.8   374.3  514.48   386.3  514.44   394.3  513.34   406.2  508.55
   414.2  507.23   422.2  508.02   450.1  508.43  457.38  507.12     470  506.44
     474  507.06     486  508.55   513.9  509.32   569.7  508.91   697.2  511.92
   760.8  512.04   780.6  513.27   796.5  512.88   820.3  513.38   851.8512.7065
   887.7  513.68  897.48513.3872  910.85513.7072   919.4  513.45   931.4  514.14
#Mann= 8 ,-1 , 0
       0     .12       0   87.48     .06       0  205.14     .12       0
  457.38    .045       0     474     .12       0   851.8     .06       0
  897.48     .12       0  910.85    .016       0
#XS Ineff= 2 , 0
                          519.09          510.73
Permanent Ineff=
       F       F
Bank Sta=457.38,474
XS Rating Curve= 0 ,0
Exp/Cntr=0.3,0.1

Type RM Length L Ch R = 1 ,3278.2  ,197,180.3,162.3
XS GIS Cut Line= 4
      2356017.26      345732.311     2355878.371      345670.462
     2355481.236       345569.55     2355271.817      345671.547
#Sta/Elev= 30
       0  531.09    31.2  529.43    46.8  527.98    97.5  521.17   124.8  518.04
     160  515.36   187.8  514.83   271.4  515.78  300.83515.0981   315.1  513.64
   319.1  512.76   327.1  508.97  341.98  500.05     347  499.02     351   499.2
   354.9  500.05   362.9  502.15   366.9   502.6   394.7   504.1  470.46504.4584
  501.05504.7016   632.9  506.82   640.8  507.16  646.86508.1228   652.6  509.18
  659.96507.7975   688.1  508.28   727.6  509.72  789.53509.8763   794.7  509.91
#Mann= 9 ,-1 , 0
       0     .06       0  300.83     .12       0  341.98    .045       0
   354.9     .12       0  470.46     .08       0  501.05     .06       0
  646.86     .12       0  659.96     .08       0  789.53     .12       0
#XS Ineff= 2 , 0
                          381.42          504.59
Permanent Ineff=
       F       F
Bank Sta=341.98,354.9
XS Rating Curve= 0 ,0
Exp/Cntr=0.3,0.1

Type RM Length L Ch R = 1 ,3098    ,80.2,79.7,80.2
XS GIS Cut Line= 2
     2356148.553       345257.05     2355266.392      345660.696
#Sta/Elev= 30
       0  511.57    51.9  510.09   119.8  507.21   219.6  504.87   319.4  503.61
   335.4  503.93  340.49504.5318   355.3  503.99   375.3  501.82   387.2  501.22
   427.2  502.23   439.2  500.68  449.26   498.6   455.1  497.75   465.4   498.6
   475.1   500.4   487.1  501.33     499  500.67     519  502.22   554.9  502.66
   590.9  503.77  661.13504.0261   698.6  504.34   738.6  505.58   814.4  506.78
  828.15507.9688   838.4  507.45  856.08507.7374  947.56 509.463   970.1   509.9
#Mann= 8 ,-1 , 0
       0     .06       0  340.49     .12       0  449.26    .045       0
   465.4     .12       0  661.13     .06       0  828.15    .016       0
  856.08     .08       0  947.56    .016       0
#XS Ineff= 2 , 0
          424.15  502.46   487.1          502.43
Permanent Ineff=
       F       F
Bank Sta=449.26,465.4
XS Rating Curve= 0 ,0
Exp/Cntr=0.3,0.1

Type RM Length L Ch R = 1 ,3018.3  ,125.7,127.4,129.6
XS GIS Cut Line= 2
     2356129.022      345194.116     2355246.861      345597.762
#Sta/Elev= 30
       0  505.62    91.8  503.57  105.38505.5511  115.79505.6002  134.33504.9702
   147.7  503.66  166.55503.1475  189.41502.5138  201.42502.4109  293.01502.3621
   327.4  502.41   359.3  501.31   371.3  501.79   375.3  501.38   383.3  498.83
  391.56497.5102   395.2  497.31   411.2  497.79   427.2  498.09  432.82499.3553
   439.2  500.62   443.1   500.8     523  500.41   586.9  502.55   686.7  503.25
   738.6  505.15  892.36507.8048   918.2  509.12   951.8 509.506   970.1  509.56
#Mann= 14 ,-1 , 0
       0     .06       0  105.38     .08       0  115.79    .016       0
  134.33     .06       0  166.55     .12       0  189.41    .016       0
  201.42     .06       0  293.01     .12       0  391.56    .016       0
   411.2    .045       0   427.2    .016       0  432.82     .06       0
  892.36    .016       0   951.8     .12       0
#XS Ineff= 2 , 0
           406.6  497.84  441.69          500.94
Permanent Ineff=
       F       F
Bank Sta=411.2,427.2
XS Rating Curve= 0 ,0
Exp/Cntr=0.3,0.1

Type RM Length L Ch R = 1 ,2890.9  ,196.6,204,211.2
XS GIS Cut Line= 3
     2356087.789       345089.95     2355410.022      345400.072
     2355232.755      345347.111
#Sta/Elev= 30
       0  498.54    43.8  498.21    91.7  499.41   135.5  499.58   147.5  500.92
  155.65500.7581  156.42500.7215  187.87500.6071   203.3  501.24   219.2  500.71
   263.1  501.42   310.9  501.19   358.7  499.88   362.7  499.46   370.7  496.78
   374.7  495.74   378.6  495.58   386.9  496.92   402.6  499.17   410.5  499.65
   438.4  499.01   470.3  499.62  507.22499.1917   526.1  498.69     570  501.07
   669.6  501.92   713.5  504.23   753.2  504.82   800.5  506.82   930.4   515.3
#Mann= 7 ,-1 , 0
       0     .06       0  155.65     .08       0  156.42     .06       0
  187.87     .12       0   370.7    .045       0   386.9     .12       0
  507.22     .06       0
#XS Ineff= 2 , 0
          262.13  501.63  478.84          500.49
Permanent Ineff=
       F       F
Bank Sta=370.7,386.9
XS Rating Curve= 0 ,0
Exp/Cntr=0.3,0.1

Type RM Length L Ch R = 1 ,2686.9  ,415.8,439.1,462
XS GIS Cut Line= 3
      2356071.21      345065.297     2355523.097      345116.376
     2355336.835      344995.852
#Sta/Elev= 30
       0  497.23    31.9  498.46    63.6498.1675   131.6  499.41   207.4   499.4
   219.4  499.87  271.96499.5719   307.2  499.99  341.63498.9141  352.39498.7326
  393.21498.3242  422.81497.3405   438.8  497.92   454.8   497.6   458.7  496.99
  465.89  494.79   478.7  494.19  484.14  494.79   498.6  497.99   538.5  498.78
  559.38500.0221   574.3  501.39   586.1   503.8   621.8  514.24   633.7   516.7
   653.5  518.67     705  521.71   720.8  522.33  752.61 522.368   772.3  521.68
#Mann= 11 ,-1 , 0
       0     .06       0    63.6     .08       0  271.96     .06       0
  341.63     .08       0  352.39     .06       0  393.21     .08       0
  422.81     .12       0  465.89    .045       0  484.14     .12       0
  559.38     .06       0  752.61     .08       0
#XS Ineff= 2 , 0
          397.11  499.16  508.57          498.87
Permanent Ineff=
       F       F
Bank Sta=465.89,484.14
XS Rating Curve= 0 ,0
Exp/Cntr=0.3,0.1

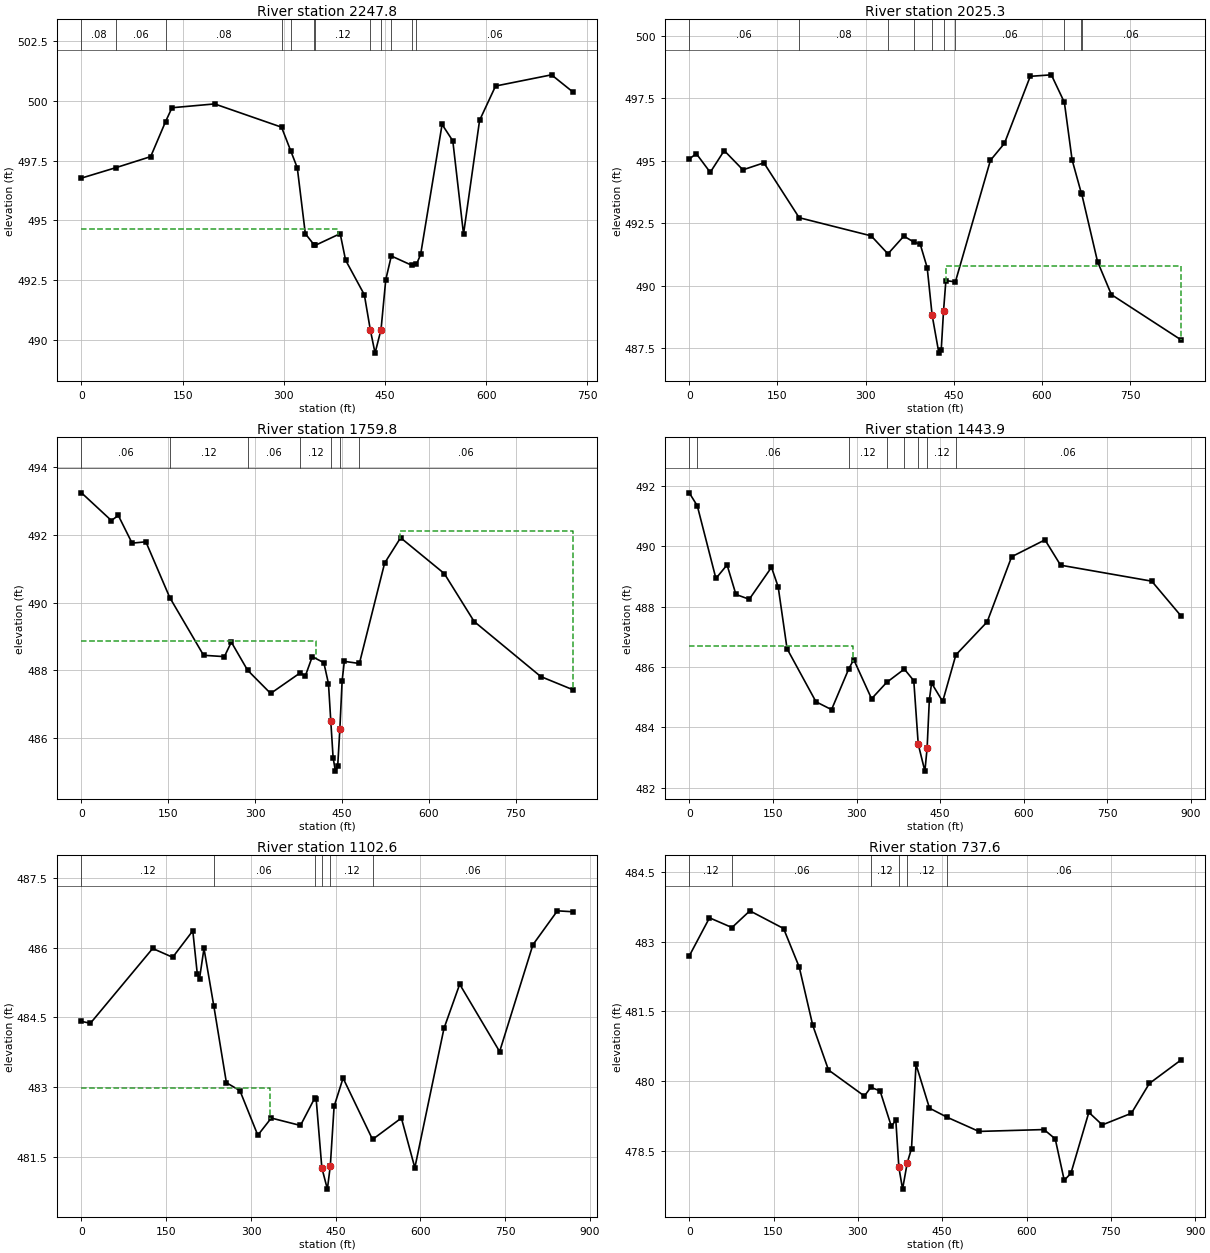
Type RM Length L Ch R = 1 ,2247.8  ,229.4,222.4,216
XS GIS Cut Line= 4
     2356082.494      344985.002     2355830.758      344853.057
     2355647.614       344622.83     2355532.147      344526.668
#Sta/Elev= 30
       0  496.77   51.57 497.212   102.6  497.67  124.75499.1427   134.2  499.72
   197.4  499.88  296.66498.9046   310.5497.8954     320   497.2   331.9  494.44
  345.09493.9636  346.99493.9541   383.6  494.44   391.6  493.33   419.4  491.88
   428.2  490.42   435.3  489.43  444.17  490.42   451.2  492.51  459.41493.5039
  490.37493.1057  496.64493.1491   502.9  493.57   534.7  499.02   550.6  498.33
   566.5  494.42   590.3  499.19     614  500.63     697   501.1   728.7  500.38
#Mann= 12 ,-1 , 0
       0     .08       0   51.57     .06       0  124.75     .08       0
  296.66     .12       0   310.5     .08       0  345.09     .06       0
  346.99     .12       0   428.2    .045       0  444.17     .12       0
  459.41     .06       0  490.37     .08       0  496.64     .06       0
#XS Ineff= 2 , 0
          379.77  494.65
Permanent Ineff=
       F       F
Bank Sta=428.2,444.17
XS Rating Curve= 0 ,0
Exp/Cntr=0.3,0.1

Type RM Length L Ch R = 1 ,2025.3  ,267.7,265.6,262.7
XS GIS Cut Line= 4
     2356225.864      344843.752     2355887.839      344593.171
     2355734.489      344472.105     2355704.022      344254.099
#Sta/Elev= 30
       0  495.06    11.9  495.28    35.7  494.53    59.5   495.4    91.3  494.63
     127  494.91  187.05492.7162   309.6  491.99   338.1491.2697   365.2  491.98
  382.27 491.739     393  491.66   404.9  490.72   413.3  488.82   424.8   487.3
   428.8  487.43   432.7  488.98   436.7   490.2  452.88490.1499   512.5  495.01
   536.4  495.69   580.3  498.37   616.2  498.43  638.36497.3284   651.5  495.03
  666.94493.7179  668.04493.6502   694.8  490.96   718.4  489.64   836.3  487.84
#Mann= 10 ,-1 , 0
       0     .06       0  187.05     .08       0   338.1     .06       0
  382.27     .12       0   413.3    .045       0   432.7     .12       0
  452.88     .06       0  638.36     .08       0  666.94     .12       0
  668.04     .06       0
#XS Ineff= 2 , 0
                          436.53          490.78
Permanent Ineff=
       F       F
Bank Sta=413.3,432.7
XS Rating Curve= 0 ,0
Exp/Cntr=0.3,0.1

Type RM Length L Ch R = 1 ,1759.8  ,314.9,315.9,316.7
XS GIS Cut Line= 5
     2356358.536      344689.863     2356303.413      344545.049
     2356060.521      344398.567     2355984.884      344351.951
     2355711.265      344183.317
#Sta/Elev= 30
       0  493.25    51.6  492.43    63.6  492.58    87.4  491.76   111.2   491.8
  152.47490.1492   210.9  488.44   246.8   488.4   258.8  488.83   286.8     488
   326.7  487.31  377.67 487.918   386.7  487.83   398.6   488.4   418.6  488.22
   426.6   487.6   430.6  486.49   434.6  485.41   438.6  485.01   442.5  485.15
   446.3  486.27   450.2  487.69     454  488.26  479.98488.1971   523.6  491.17
   551.2  491.92   626.6  490.86   678.2  489.44   793.3  487.81   848.8  487.42
#Mann= 7 ,-1 , 0
       0     .06       0  152.47     .12       0   286.8     .06       0
  377.67     .12       0   430.6    .045       0   446.3     .12       0
  479.98     .06       0
#XS Ineff= 2 , 0
          404.54  488.85  550.05          492.12
Permanent Ineff=
       F       F
Bank Sta=430.6,446.3
XS Rating Curve= 0 ,0
Exp/Cntr=0.3,0.1

Type RM Length L Ch R = 1 ,1443.9  ,355.1,341.2,327.4
XS GIS Cut Line= 3
     2356603.328      344399.932     2356167.564      344104.793
     2355815.133      344061.391
#Sta/Elev= 30
       0  491.78   14.41491.3496    47.8  488.94    67.8  489.39    83.7  488.41
   107.6  488.25   147.5  489.31   159.5  488.66   175.4  486.61   227.3  484.85
   255.2  484.59  285.85485.9331     295  486.25     327  484.95  353.91485.4902
  385.73 485.934   402.7  485.55   410.7  483.44   422.6  482.55   426.6  483.31
   430.6  484.91   434.6  485.47   454.5  484.86  478.18486.4048   534.3   487.5
   578.2  489.66     638  490.22     666  489.38   829.5  488.85   881.4  487.71
#Mann= 8 ,-1 , 0
       0     .12       0   14.41     .06       0  285.85     .12       0
  353.91     .06       0  385.73     .12       0   410.7    .045       0
   426.6     .12       0  478.18     .06       0
#XS Ineff= 2 , 0
          293.09  486.71
Permanent Ineff=
       F       F
Bank Sta=410.7,426.6
XS Rating Curve= 0 ,0
Exp/Cntr=0.3,0.1

Type RM Length L Ch R = 1 ,1102.6  ,358.8,365,370.5
XS GIS Cut Line= 4
     2356746.861      343765.948     2356587.355      343842.988
     2356099.087      343849.399     2355947.164      343712.779
#Sta/Elev= 30
       0  484.41    15.8  484.37     126  485.98   161.4  485.79     197  486.36
   204.9  485.44   208.9  485.33   216.8  485.98  234.23484.7405   256.5  483.09
   280.4  482.92   312.1  481.96   335.9  482.33   387.6  482.17   412.7482.7567
   415.3  482.75   425.4  481.26   435.2   480.8   440.4   481.3   447.1  482.58
     463  483.19  515.14481.8694   566.2  482.33     590  481.26   641.6  484.26
   669.4  485.21   740.1  483.76     799  486.06   842.3  486.79   869.8  486.77
#Mann= 6 ,-1 , 0
       0     .12       0  234.23     .06       0   412.7     .12       0
   425.4    .045       0   440.4     .12       0  515.14     .06       0
#XS Ineff= 2 , 0
          334.37  482.97
Permanent Ineff=
       F       F
Bank Sta=425.4,440.4
XS Rating Curve= 0 ,0
Exp/Cntr=0.3,0.1

Type RM Length L Ch R = 1 ,737.6   ,300.8,295.8,290.8
XS GIS Cut Line= 3
     2356782.147      343594.377     2356134.022       343436.49
     2356032.147      343616.946
#Sta/Elev= 30
       0  482.69      36  483.51   75.99483.3009   107.8  483.66   167.8  483.28
   195.7  482.45   219.7   481.2   247.7  480.24   311.6  479.68   323.1479.8675
   339.5  479.79   359.5  479.03   367.5  479.16   372.9  478.15   379.5  477.68
   387.9  478.25   395.4  478.55   403.4  480.36   427.4  479.42  458.92479.2236
   515.3  478.92   631.1  478.96   651.1  478.76   667.1  477.87     679  478.02
   710.9  479.33   734.8  479.06   786.6  479.31   818.5  479.95   874.3  480.45
#Mann= 6 ,-1 , 0
       0     .12       0   75.99     .06       0   323.1     .12       0
   372.9    .045       0   387.9     .12       0  458.92     .06       0
Bank Sta=372.9,387.9
XS Rating Curve= 0 ,0
Exp/Cntr=0.3,0.1

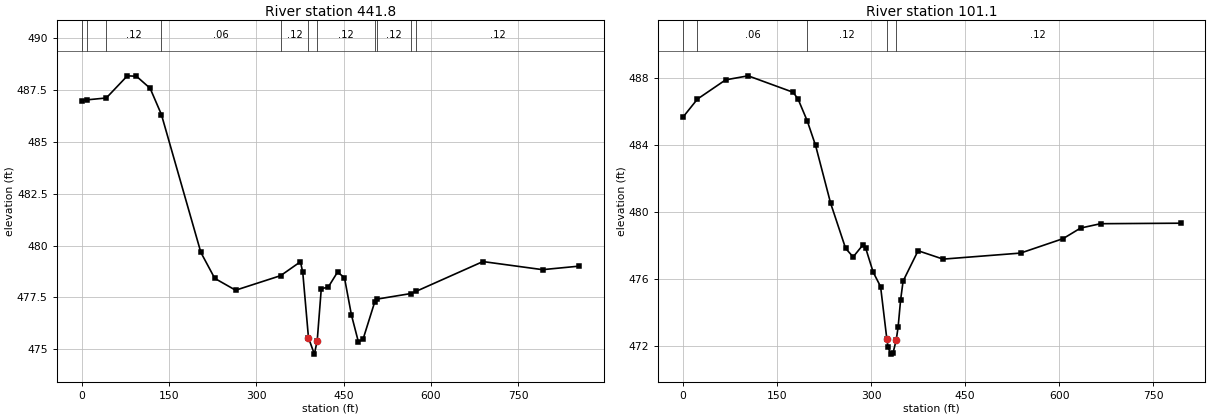
Type RM Length L Ch R = 1 ,441.8   ,337.1,340.7,340
XS GIS Cut Line= 4
     2356910.576      343189.898     2356799.085      343276.076
     2356321.923      343256.918     2356107.016      343355.019
#Sta/Elev= 30
       0  486.99    9.15487.0235    42.1487.1125    78.3  488.18    93.9  488.16
   117.4  487.58  136.81486.3161   204.6  479.67   228.5  478.42   264.3  477.85
  341.65478.5512   375.7  479.22   379.7  478.71   389.5  475.56   399.6  474.77
   404.5  475.41   411.5  477.92   423.5     478   439.4  478.72   451.3  478.46
   463.3  476.66   475.2  475.37   483.2  475.48  503.51477.2979  506.99477.4197
  565.77477.6905  574.39477.7946   689.3  479.23   791.7  478.84   854.7  479.01
#Mann= 11 ,-1 , 0
       0     .12       0    9.15     .06       0    42.1     .12       0
  136.81     .06       0  341.65     .12       0   389.5    .045       0
   404.5     .12       0  503.51     .06       0  506.99     .12       0
  565.77     .06       0  574.39     .12       0
Bank Sta=389.5,404.5
XS Rating Curve= 0 ,0
Exp/Cntr=0.3,0.1

Type RM Length L Ch R = 1 ,101.1   ,100.7,101.1,102.2
XS GIS Cut Line= 2
     2356968.866      343010.957     2356176.765      342963.214
#Sta/Elev= 30
       0  485.67   22.88486.7365    67.8  487.88   103.7  488.12   175.5  487.14
   183.4  486.73  198.05485.4285   211.3  483.97   235.3  480.53   259.2  477.84
   271.2  477.33   287.1  478.06   291.1  477.87   303.1  476.43     315  475.56
   324.9  472.46     327  471.95     331  471.54     335  471.63   339.9  472.38
   342.9  473.13   346.9  474.76   350.9  475.89   374.8   477.7   414.7   477.2
   538.3  477.56   606.1  478.42     634  479.05   665.9  479.31   793.5  479.34
#Mann= 5 ,-1 , 0
       0     .12       0   22.88     .06       0  198.05     .12       0
   324.9    .045       0   339.9     .12       0
Bank Sta=324.9,339.9
XS Rating Curve= 0 ,0
Exp/Cntr=0.3,0.1

Chan Stop Cuts=-1
Use User Specified Reach Order=0
Composite Channel Slope=5